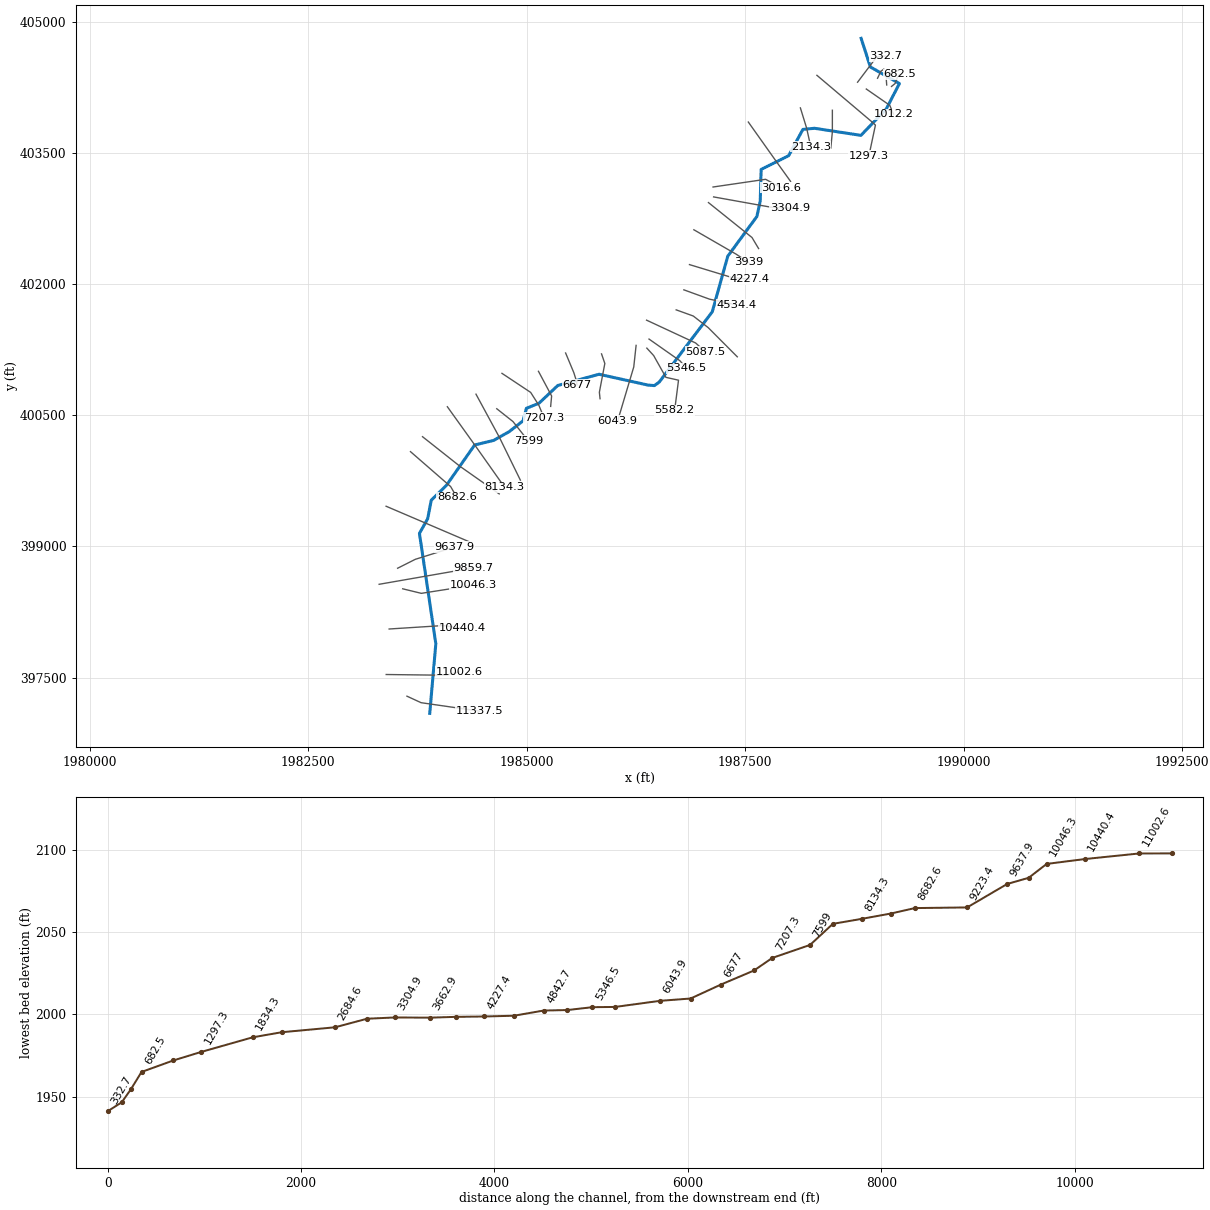
--- GladeCrk1.prj (project) ---

Proj Title=GladeCrk1
Current Plan=p01
Default Exp/Contr=0,0
English Units
Geom File=g01
Flow File=f01
Plan File=p01
BEGIN DESCRIPTION:
END DESCRIPTION:
DSS Export Rating Curves= 0
DSS Export Rating Curve Sorted= 0
DSS Export Volume Flow Curves= 0
DXF OffsetX= 0
DXF OffsetY= 0
DXF ScaleX= 0
DXF ScaleY= 0

--- GladeCrk1.p01 (plan) ---

Plan Title=Floodplain
Program Version=4.00
Geom File=g01
Flow File=f01
K Sum by GR=0
Std Step Tol=0.01
Critical Tol=0.01
Num of Std Step Trials=20
Max Error Tol=0.3
Flow Tol Ratio=0.001
Split Flow NTrial=30
Split Flow Tol=0.02
Split Flow Ratio=0.02
Log Output Level=0
Friction Slope Method=1
Unsteady Friction Slope Method=2
Unsteady Bridges Friction Slope Method=1
Global Log Level=0
CheckData=False
Run HTab=0
Run UNet=0
Run PostProcess=0
UNET Theta=0
UNET Theta Warmup=0
UNET ZTol=0
UNET ZSATol=0
UNET MxIter=0
UNET MaxInSteps=0
UNET DtIC=0
UNET DtMin=0
UNET MaxCRTS=0
UNET WFStab=0
UNET SFStab=0
UNET WFX=0
UNET SFX=0
UNET DSS MLevel=0
UNET DZMax Abort=0
UNET Convert EG Bridges=0
UNET Use Existing IB Tables=0
UNET Froude Limit=0
UNET Froude Power=0
Write IC File=0
Echo Input=False
Echo Output=False
Write Detailed=0

--- GladeCrk1.f01 (steady flow) ---

Flow Title=NFF Regression Equation
Program Version=4.10
Number of Profiles= 1
Profile Names=P100yr
River Rch & RM=GladeCrk1,Main            ,11337.5
557.7732
River Rch & RM=GladeCrk1,Main            ,9223.4
583.1633
River Rch & RM=GladeCrk1,Main            ,5582.2
966.7197
River Rch & RM=GladeCrk1,Main            ,1834.3
     998
River Rch & RM=GladeCrk1,Main            ,1297.3
1140.677
River Rch & RM=GladeCrk1,Main            ,104.8
1180.441
Boundary for River Rch & Prof#=GladeCrk1,Main            , 1
Up Type= 0
Dn Type= 3
Dn Slope=0.054882
DSS Import GetInterval= 0
DSS Import GetPeak= 0
DSS Import FillOption= 0

--- GladeCrk1.g01 (geometry) ---

Geom Title=USGS 3m DEM
Program Version=4.00

River Reach=GladeCrk1     ,Main
Reach XY= 30
     1983892.800      397089.799     1983962.245      397886.674
     1983774.745      399149.101     1983868.495      399315.493
     1983910.161      399529.035     1984083.773      399699.174
     1984406.689      400160.979     1984623.703      400213.062
     1984802.523      400313.757     1984959.977      400436.671
     1984998.488      400580.220     1985142.800      400638.410
     1985358.078      400841.535     1985830.301      400970.007
     1986385.856      400846.743     1986463.197      400840.206
     1986517.800      400879.729     1987125.439      401685.285
     1987302.523      402320.701     1987635.856      402775.563
     1987674.050      402952.646     1987684.467      403313.757
     1987999.115      403470.706     1988162.091      403771.608
     1988295.578      403784.243     1988826.300      403703.202
     1989115.023      404002.993     1989266.371      404296.377
     1988934.263      404485.985     1988828.430      404813.438

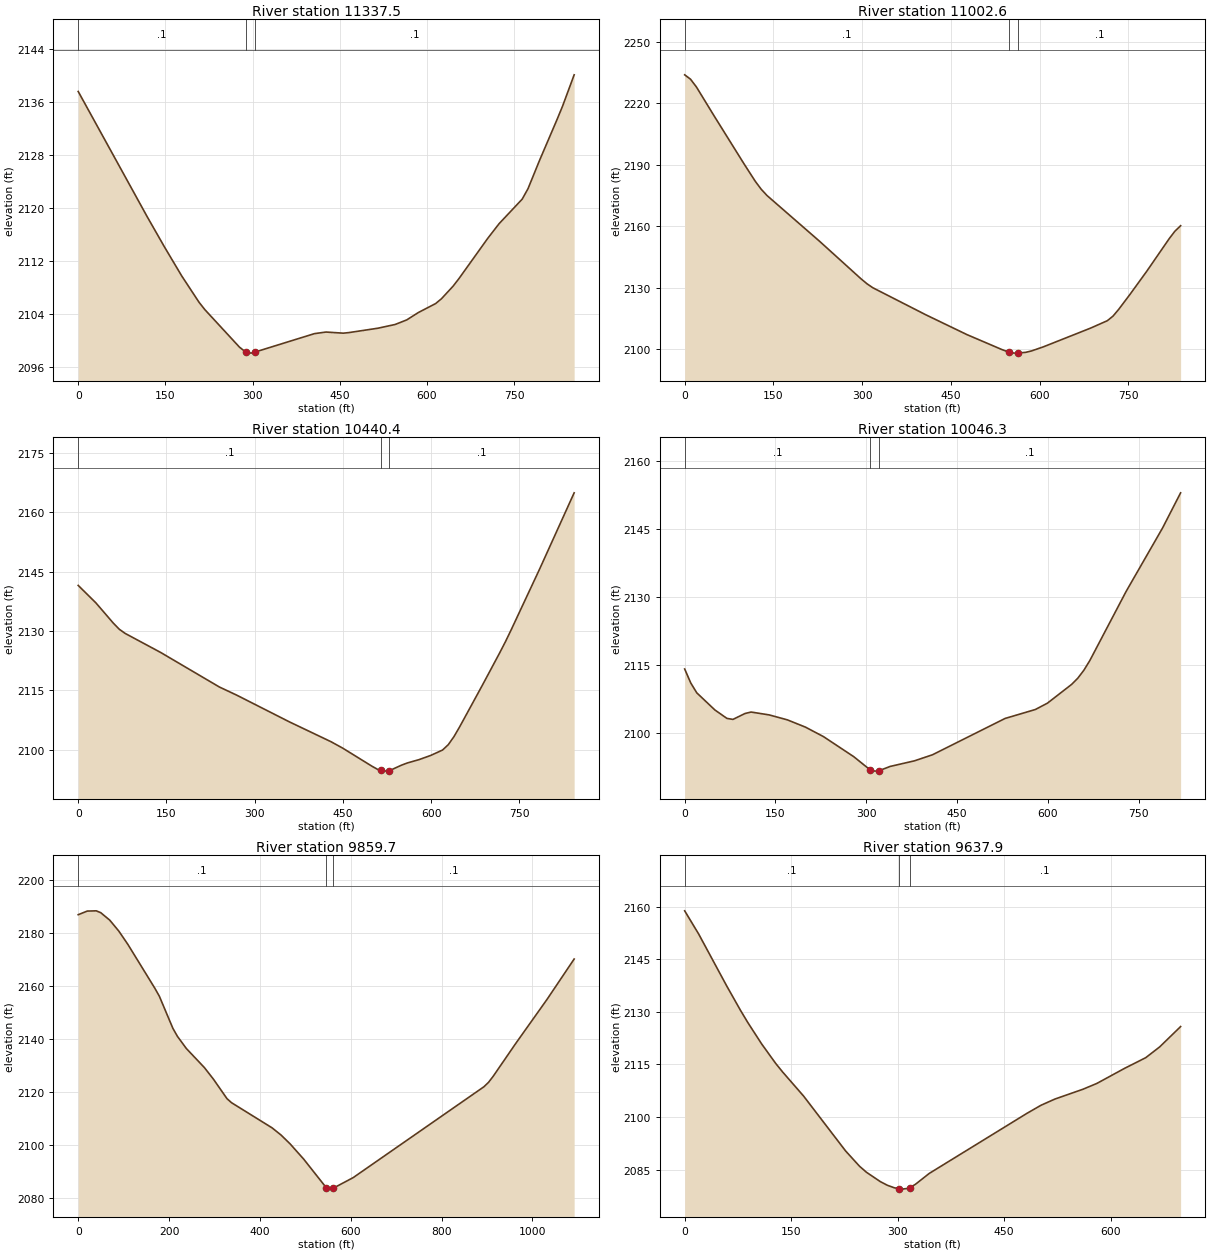
Type RM Length L Ch R = 1 ,11337.5,331.9,334.8,337.8
XS GIS Cut Line= 3
     1983631.784      397286.559     1983793.523      397212.083
     1984461.838      397115.527
#Sta/Elev= 30
       0 2137.63   118.7 2118.68   148.4 2114.11   178.1 2109.72   207.8 2105.75
   217.8 2104.63   277.4 2098.95   288.4 2098.19   297.2 2098.04   303.4 2098.18
   406.5 2100.99   426.3 2101.23   456.1 2101.06   466.0 2101.15   515.7 2101.81
   545.5 2102.38   565.3 2103.07   585.2 2104.18   615.0 2105.54   624.9 2106.26
   644.8 2108.15   654.7 2109.27   704.4 2115.38   724.2 2117.63   763.9 2121.34
   773.9 2122.92   793.7 2127.19   823.5 2133.31   833.5 2135.44   853.3 2140.15
#Mann= 3 , 0 , 0
       0     0.1       0   288.4   0.045       0   303.4     0.1       0
Bank Sta=   288.4,   303.4
Exp/Cntr=0.3,0.1

Type RM Length L Ch R = 1 ,11002.6,560.6,562.3,564
XS GIS Cut Line= 3
     1983394.456      397534.524     1984080.557      397525.891
     1984228.042      397564.289
#Sta/Elev= 30
       0 2233.99     9.9 2231.85    19.9 2228.04    49.7 2213.96    99.4 2190.93
   119.3 2182.00   129.3 2178.12   139.2 2175.02   228.7 2152.50   298.3 2134.28
   308.3 2131.89   318.2 2129.94   407.7 2116.74   477.3 2107.05   537.0 2099.67
   548.9 2098.41   556.9 2098.00   563.9 2098.05   576.8 2098.39   586.7 2099.09
   606.6 2101.08   686.2 2110.20   714.7 2113.85   724.3 2116.09   733.8 2119.35
   752.8 2126.63   781.4 2138.03   819.5 2154.01   829.0 2157.59   838.6 2160.26
#Mann= 3 , 0 , 0
       0     0.1       0   548.9   0.045       0   563.9     0.1       0
Bank Sta=   548.9,   563.9
Exp/Cntr=0.3,0.1

Type RM Length L Ch R = 1 ,10440.4,392,394,396.1
XS GIS Cut Line= 3
     1983427.862      398055.181     1984046.027      398094.645
     1984267.270      398061.694
#Sta/Elev= 30
       0 2141.50    30.0 2137.10    59.9 2131.94    69.9 2130.42    79.9 2129.37
   139.9 2124.59   239.8 2115.86   269.8 2113.76   359.7 2106.99   429.6 2102.04
   449.6 2100.41   499.5 2095.83   509.5 2095.00   514.1 2094.82   519.5 2094.60
   529.1 2094.72   549.5 2096.10   559.5 2096.66   579.5 2097.51   599.4 2098.57
   619.4 2099.93   629.2 2101.29   638.9 2103.34   648.6 2105.82   687.5 2116.41
   716.7 2124.52   726.4 2127.32   736.1 2130.30   784.8 2145.76   843.1 2164.88
#Mann= 3 , 0 , 0
       0     0.1       0   514.1   0.045       0   529.1     0.1       0
Bank Sta=   514.1,   529.1
Exp/Cntr=0.3,0.1

Type RM Length L Ch R = 1 ,10046.3,186.2,186.6,187
XS GIS Cut Line= 3
     1983583.142      398515.164     1983796.323      398463.198
     1984389.045      398555.970
#Sta/Elev= 30
       0 2114.15    10.0 2111.08    20.0 2108.89    49.9 2105.12    69.8 2103.26
    79.8 2103.04    99.7 2104.34   109.7 2104.66   139.6 2104.03   169.6 2102.94
   199.5 2101.34   229.4 2099.24   279.4 2094.82   306.3 2091.93   309.4 2091.66
   319.4 2091.64   321.3 2091.74   339.4 2092.67   379.4 2093.90   409.4 2095.24
   529.4 2103.25   579.4 2105.22   599.4 2106.62   639.4 2110.76   649.4 2112.10
   659.4 2113.84   669.4 2116.01   729.4 2131.25   789.4 2145.18   819.4 2152.97
#Mann= 3 , 0 , 0
       0     0.1       0   306.3   0.045       0   321.3     0.1       0
Bank Sta=   306.3,   321.3
Exp/Cntr=0.3,0.1

Type RM Length L Ch R = 1 ,9859.7,218.9,221.8,224.8
XS GIS Cut Line= 3
     1983313.594      398566.741     1983851.473      398660.557
     1984389.353      398754.373
#Sta/Elev= 30
       0 2187.05    19.8 2188.41    39.7 2188.51    49.6 2187.81    69.5 2184.97
    89.4 2180.84   109.2 2175.85   168.8 2159.19   178.7 2156.17   208.5 2144.02
   218.4 2141.02   238.2 2136.38   278.0 2129.15   297.8 2124.78   327.6 2117.42
   337.5 2115.90   426.9 2106.37   446.7 2103.64   466.6 2100.30   496.4 2094.55
   546.0 2083.77   555.9 2083.18     561 2083.48   605.6 2087.55   893.4 2121.93
   903.4 2123.58   913.3 2125.78   963.0 2138.22  1032.4 2155.02  1092.0 2170.27
#Mann= 3 , 0 , 0
       0     0.1       0     546   0.045       0     561     0.1       0
Bank Sta=     546,     561
Exp/Cntr=0.3,0.1

Type RM Length L Ch R = 1 ,9637.9,430.2,414.3,398.5
XS GIS Cut Line= 3
     1983525.086      398750.529     1983727.499      398852.520
     1984177.831      398993.739
#Sta/Elev= 30
       0 2158.82    19.7 2152.21    59.1 2137.43    78.8 2130.37    88.7 2127.03
   108.4 2120.86   128.1 2115.32   138.0 2112.84   167.5 2105.98   226.7 2090.32
   246.3 2085.96   256.2 2084.22   275.8 2081.55   285.6 2080.52   295.5 2079.80
   301.8 2079.56   305.3 2079.43   315.2 2079.64   316.8 2079.83   325.0 2080.80
   344.6 2083.92   482.3 2101.07   502.0 2103.36   521.6 2105.13   561.0 2107.92
   580.6 2109.58   620.0 2113.92   649.4 2116.92   669.1 2120.00   698.6 2125.80
#Mann= 3 , 0 , 0
       0     0.1       0   301.8   0.045       0   316.8     0.1       0
Bank Sta=   301.8,   316.8
Exp/Cntr=0.3,0.1

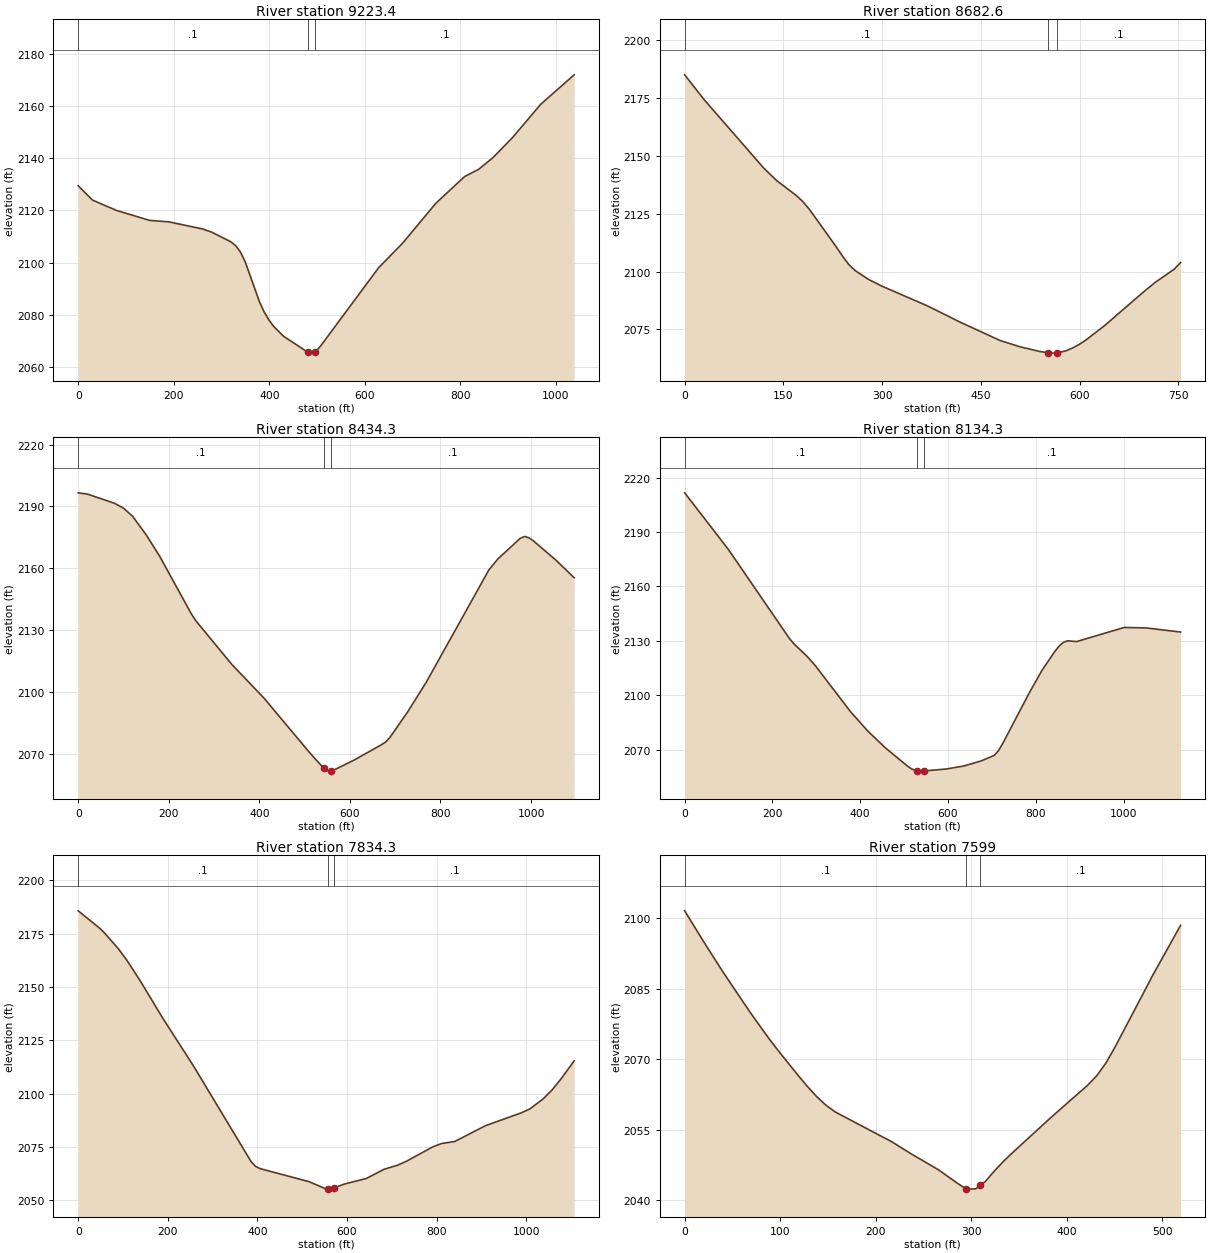
Type RM Length L Ch R = 1 ,9223.4,547.8,540.6,533.4
XS GIS Cut Line= 2
     1983393.281      399459.762     1984347.830      399051.876
#Sta/Elev= 30
       0 2129.53    29.9 2124.00    79.8 2120.04   149.7 2116.18   189.6 2115.63
   259.5 2112.93   279.5 2111.66   319.4 2107.97   329.4 2106.53   339.4 2104.07
   349.3 2100.38   379.3 2084.94   389.3 2080.93   399.2 2077.89   409.2 2075.42
   429.2 2071.72   480.2 2065.55   489.1 2065.16   495.2 2065.73   499.1 2066.09
   509.0 2068.30   628.8 2098.00   678.7 2107.37   748.6 2122.78   808.5 2133.01
   838.4 2135.85   868.4 2140.38   908.3 2147.89   968.2 2160.86  1038.0 2172.15
#Mann= 3 , 0 , 0
       0     0.1       0   480.2   0.045       0   495.2     0.1       0
Bank Sta=   480.2,   495.2
Exp/Cntr=0.3,0.1

Type RM Length L Ch R = 1 ,8682.6,247.3,248.3,250.7
XS GIS Cut Line= 3
     1983672.299      400084.517     1984131.554      399685.059
     1984204.506      399560.184
#Sta/Elev= 30
       0 2185.11    29.9 2174.26   119.7 2144.90   139.7 2139.37   169.6 2132.92
   179.6 2130.26   189.6 2126.88   229.5 2111.02   239.5 2106.80   249.5 2103.02
   259.4 2100.37   279.4 2096.62   299.4 2093.75   369.2 2085.13   419.1 2078.06
   479.0 2070.24   508.9 2067.53   538.8 2065.52   551.2 2064.93   558.8 2064.76
   566.2 2064.89   578.7 2065.70   588.7 2066.92   598.7 2068.42   608.7 2070.26
   637.6 2076.60   695.4 2090.84   714.7 2095.35   743.6 2101.07   753.3 2103.95
#Mann= 3 , 0 , 0
       0     0.1       0   551.2   0.045       0   566.2     0.1       0
Bank Sta=   551.2,   566.2
Exp/Cntr=0.3,0.1

Type RM Length L Ch R = 1 ,8434.3,306.4,300,292.1
XS GIS Cut Line= 3
     1983809.987      400255.582     1984241.283      399914.457
     1984687.574      399601.103
#Sta/Elev= 30
       0 2196.62    20.0 2196.03    80.0 2191.56   100.0 2189.17   120.0 2185.26
   150.0 2176.25   180.0 2165.78   250.0 2137.75   260.0 2134.42   339.9 2113.09
   409.9 2097.01   509.9 2070.72   542.4 2062.80   549.9 2061.68   557.4 2061.50
   559.8 2061.44   609.4 2066.82   668.9 2074.17   678.8 2075.58   688.7 2077.89
   728.4 2090.50   768.0 2104.39   906.8 2159.14   926.6 2164.47   976.2 2174.55
   986.1 2175.42   996.1 2174.69  1006.0 2173.14  1055.6 2163.80  1095.2 2155.38
#Mann= 3 , 0 , 0
       0     0.1       0   542.4   0.045       0   557.4     0.1       0
Bank Sta=   542.4,   557.4
Exp/Cntr=0.3,0.1

Type RM Length L Ch R = 1 ,8134.3,302.8,299.8,296.1
XS GIS Cut Line= 3
     1984094.215      400598.221     1984407.264      400161.362
     1984749.255      399677.340
#Sta/Elev= 30
       0 2211.60    99.5 2180.42   238.9 2131.27   248.8 2128.43   278.7 2121.53
   298.6 2116.08   378.2 2090.90   418.0 2080.11   457.8 2070.97   507.6 2061.01
   517.5 2059.38   529.9 2058.34   537.4 2058.22   544.9 2058.31   596.7 2059.41
   636.2 2061.05   675.7 2063.86   705.4 2066.87   715.2 2069.50   725.1 2073.59
   784.4 2100.97   814.0 2113.68   843.6 2124.21   853.5 2127.20   863.4 2129.28
   873.3 2130.04   893.0 2129.62  1001.7 2137.40  1051.1 2137.15  1130.1 2134.88
#Mann= 3 , 0 , 0
       0     0.1       0   529.9   0.045       0   544.9     0.1       0
Bank Sta=   529.9,   544.9
Exp/Cntr=0.3,0.1

Type RM Length L Ch R = 1 ,7834.3,231.5,235.4,240.2
XS GIS Cut Line= 3
     1984421.806      400741.976     1984690.875      400245.934
     1984929.450      399758.411
#Sta/Elev= 30
       0 2185.73    49.5 2177.30    59.4 2175.19    89.1 2168.07   108.9 2162.48
   138.6 2152.82   188.1 2135.59   257.4 2112.93   386.1 2068.02   396.0 2065.82
   405.9 2064.78   514.8 2058.68   554.4 2055.16   556.8 2055.17   571.8 2055.83
   593.9 2057.52   643.3 2060.17   682.7 2064.46   712.4 2066.35   732.1 2068.16
   791.3 2074.97   811.0 2076.55   840.6 2077.51   909.7 2084.98   988.7 2090.91
  1008.4 2092.80  1038.0 2097.53  1057.7 2101.67  1077.5 2106.79  1107.1 2115.32
#Mann= 3 , 0 , 0
       0     0.1       0   556.8   0.045       0   571.8     0.1       0
Bank Sta=   556.8,   571.8
Exp/Cntr=0.3,0.1

Type RM Length L Ch R = 1 ,7599,393.8,391.3,388.5
XS GIS Cut Line= 3
     1984659.545      400575.392     1984845.161      400428.592
     1985020.438      400206.654
#Sta/Elev= 30
       0 2101.55    19.7 2095.04    39.4 2088.76    69.0 2079.83    88.7 2074.25
    98.6 2071.65   118.3 2066.67   128.2 2064.27   138.0 2062.08   147.9 2060.21
   157.8 2058.75   216.9 2052.42   236.6 2049.93   265.9 2046.45   285.4 2043.63
   294.8 2042.39   295.2 2042.34   304.9 2042.40   309.8 2043.16   314.7 2043.92
   324.4 2046.19   334.2 2048.31   343.9 2050.18   382.9 2057.44   421.9 2064.40
   431.7 2066.47   441.4 2069.21   451.2 2072.70   490.2 2087.80   519.5 2098.47
#Mann= 3 , 0 , 0
       0     0.1       0   294.8   0.045       0   309.8     0.1       0
Bank Sta=   294.8,   309.8
Exp/Cntr=0.3,0.1

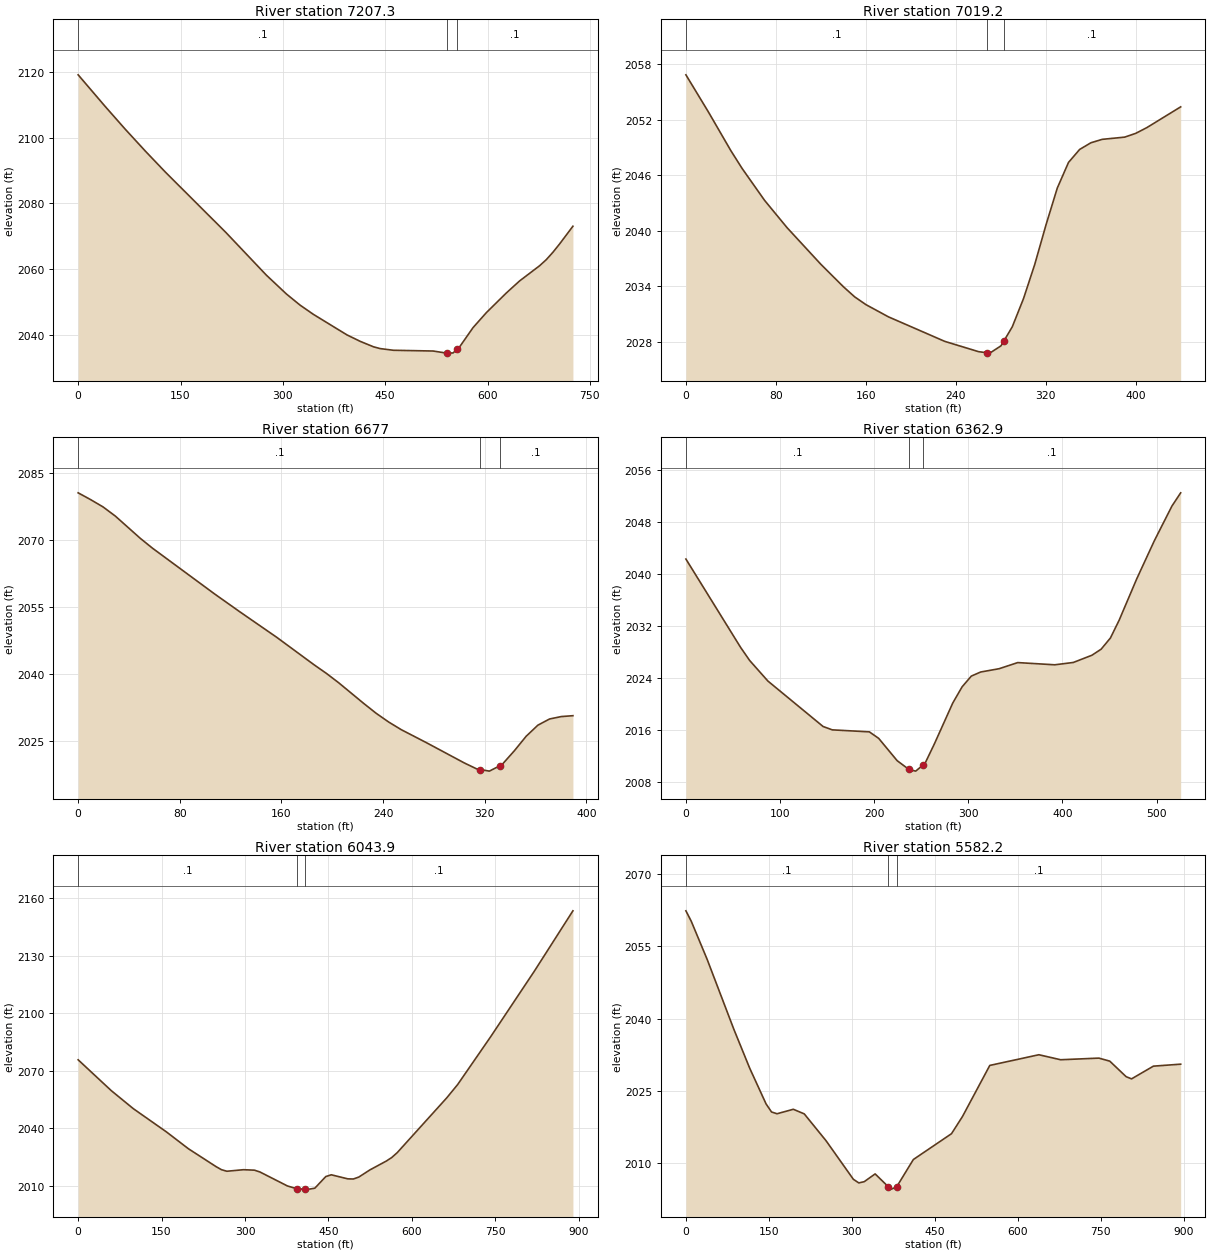
Type RM Length L Ch R = 1 ,7207.3,190.1,188.1,186.5
XS GIS Cut Line= 4
     1984719.171      400980.220     1985047.363      400762.274
     1985141.259      400614.620     1985200.884      400470.262
#Sta/Elev= 30
       0 2119.08    39.4 2109.51    68.9 2102.56    98.5 2095.87   128.0 2089.45
   216.7 2071.08   275.8 2058.14   305.3 2052.39   325.0 2049.05   344.7 2046.21
   394.0 2039.95   413.4 2037.99   432.8 2036.34   442.6 2035.79   462.0 2035.28
   520.3 2035.05   539.8 2034.41   540.8 2034.42   549.5 2034.46   555.8 2035.69
   559.2 2036.36   578.7 2042.16   598.2 2046.72   627.5 2052.71   647.0 2056.38
   676.3 2061.00   686.1 2062.85   695.8 2065.10   705.6 2067.63   725.1 2073.02
#Mann= 3 , 0 , 0
       0     0.1       0   540.8   0.045       0   555.8     0.1       0
Bank Sta=   540.8,   555.8
Exp/Cntr=0.3,0.1

Type RM Length L Ch R = 1 ,7019.2,346.1,342.1,337.8
XS GIS Cut Line= 3
     1985136.551      401003.756     1985287.185      400721.318
     1985276.201      400602.067
#Sta/Elev= 30
       0 2056.85    20.0 2052.84    40.0 2048.65    50.0 2046.73    70.0 2043.28
    90.0 2040.33   120.0 2036.38   140.0 2033.96   150.0 2032.87   160.0 2032.03
   180.0 2030.71   230.1 2028.06   260.1 2026.95   267.4 2026.83   270.1 2026.79
   280.1 2027.58   282.4 2028.05   290.1 2029.63   300.1 2032.68   310.1 2036.38
   320.1 2040.65   330.1 2044.61   340.1 2047.39   350.0 2048.79   360.0 2049.51
   370.0 2049.88   390.0 2050.12   399.9 2050.53   409.9 2051.16   439.8 2053.39
#Mann= 3 , 0 , 0
       0     0.1       0   267.4   0.045       0   282.4     0.1       0
Bank Sta=   267.4,   282.4
Exp/Cntr=0.3,0.1

Type RM Length L Ch R = 1 ,6677,325,313.9,303.1
XS GIS Cut Line= 4
     1985447.219      401213.242     1985541.326      400987.766
     1985571.178      400893.145     1985577.455      400847.641
#Sta/Elev= 29
       0 2080.62     9.8 2079.10    19.6 2077.46    29.3 2075.40    48.9 2070.42
    58.6 2068.19   107.5 2057.93   127.0 2054.00   156.4 2048.21   185.7 2042.07
   195.5 2040.12   205.2 2038.01   224.8 2033.40   234.6 2031.19   244.3 2029.26
   254.2 2027.54   274.1 2024.61   303.9 2020.07   313.8 2018.71   316.7 2018.57
   323.7 2018.22   331.7 2019.38   333.6 2019.65   343.5 2022.82   352.7 2026.04
   361.9 2028.52   371.1 2029.91   380.3 2030.45   389.5 2030.65
#Mann= 3 , 0 , 0
       0     0.1       0   316.7   0.045       0   331.7     0.1       0
Bank Sta=   316.7,   331.7
Exp/Cntr=0.3,0.1

Type RM Length L Ch R = 1 ,6362.9,321.2,318.9,316.6
XS GIS Cut Line= 4
     1985858.337      401203.032     1985895.996      401093.195
     1985833.517      400764.226     1985841.077      400689.936
#Sta/Elev= 30
       0 2042.35    58.1 2028.76    67.7 2026.75    87.1 2023.58   145.7 2016.59
   155.5 2016.07   194.9 2015.76   204.8 2014.76   224.4 2011.33   236.9 2009.98
   244.1 2009.72   251.9 2010.66   254.0 2010.91   263.8 2013.86   283.5 2020.20
   293.4 2022.69   303.2 2024.34   313.1 2024.97   332.8 2025.48   352.5 2026.42
   391.9 2026.08   411.6 2026.44   431.3 2027.55   441.1 2028.48   451.0 2030.21
   460.3 2032.96   479.0 2039.33   497.6 2045.16   516.3 2050.50   525.6 2052.54
#Mann= 3 , 0 , 0
       0     0.1       0   236.9   0.045       0   251.9     0.1       0
Bank Sta=   236.9,   251.9
Exp/Cntr=0.3,0.1

Type RM Length L Ch R = 1 ,6043.9,444.1,462.1,480.1
XS GIS Cut Line= 3
     1986253.750      401300.316     1986227.076      401053.968
     1986043.491      400438.880
#Sta/Elev= 30
       0 2075.68    59.5 2059.63    99.1 2050.24   158.6 2038.14   198.2 2029.35
   247.8 2020.05   257.7 2018.42   267.5 2017.61   297.2 2018.41   316.9 2018.17
   326.8 2017.24   376.2 2009.96   393.2 2008.48   408.2 2008.30   415.7 2008.29
   425.6 2008.78   445.3 2014.84   455.2 2015.76   484.8 2013.65   494.7 2013.56
   504.6 2014.56   524.3 2018.25   553.9 2022.88   563.8 2024.73   573.7 2027.28
   662.6 2055.78   682.3 2062.73   741.6 2087.62   820.6 2121.98   889.7 2153.31
#Mann= 3 , 0 , 0
       0     0.1       0   393.2   0.045       0   408.2     0.1       0
Bank Sta=   393.2,   408.2
Exp/Cntr=0.3,0.1

Type RM Length L Ch R = 1 ,5582.2,224.7,235.2,245.8
XS GIS Cut Line= 5
     1986376.533      401268.934     1986454.579      401183.973
     1986594.637      400934.716     1986739.047      400901.998
     1986695.060      400559.701
#Sta/Elev= 30
       0 2062.41     9.6 2060.26    38.5 2052.30    86.5 2037.85   115.4 2029.70
   144.9 2022.30   154.8 2020.62   164.7 2020.25   194.2 2021.18   214.0 2020.22
   253.4 2014.64   302.7 2006.64   312.6 2005.88   322.4 2006.14   342.1 2007.75
   366.2 2005.06   371.7 2004.59   381.2 2005.10   411.2 2010.74   480.2 2016.11
   500.0 2019.67   549.4 2030.29   638.1 2032.51   677.5 2031.47   746.6 2031.81
   766.3 2031.18   795.9 2027.95   805.7 2027.50   845.2 2030.14   894.5 2030.55
#Mann= 3 , 0 , 0
       0     0.1       0   366.2   0.045       0   381.2     0.1       0
Bank Sta=   366.2,   381.2
Exp/Cntr=0.3,0.1

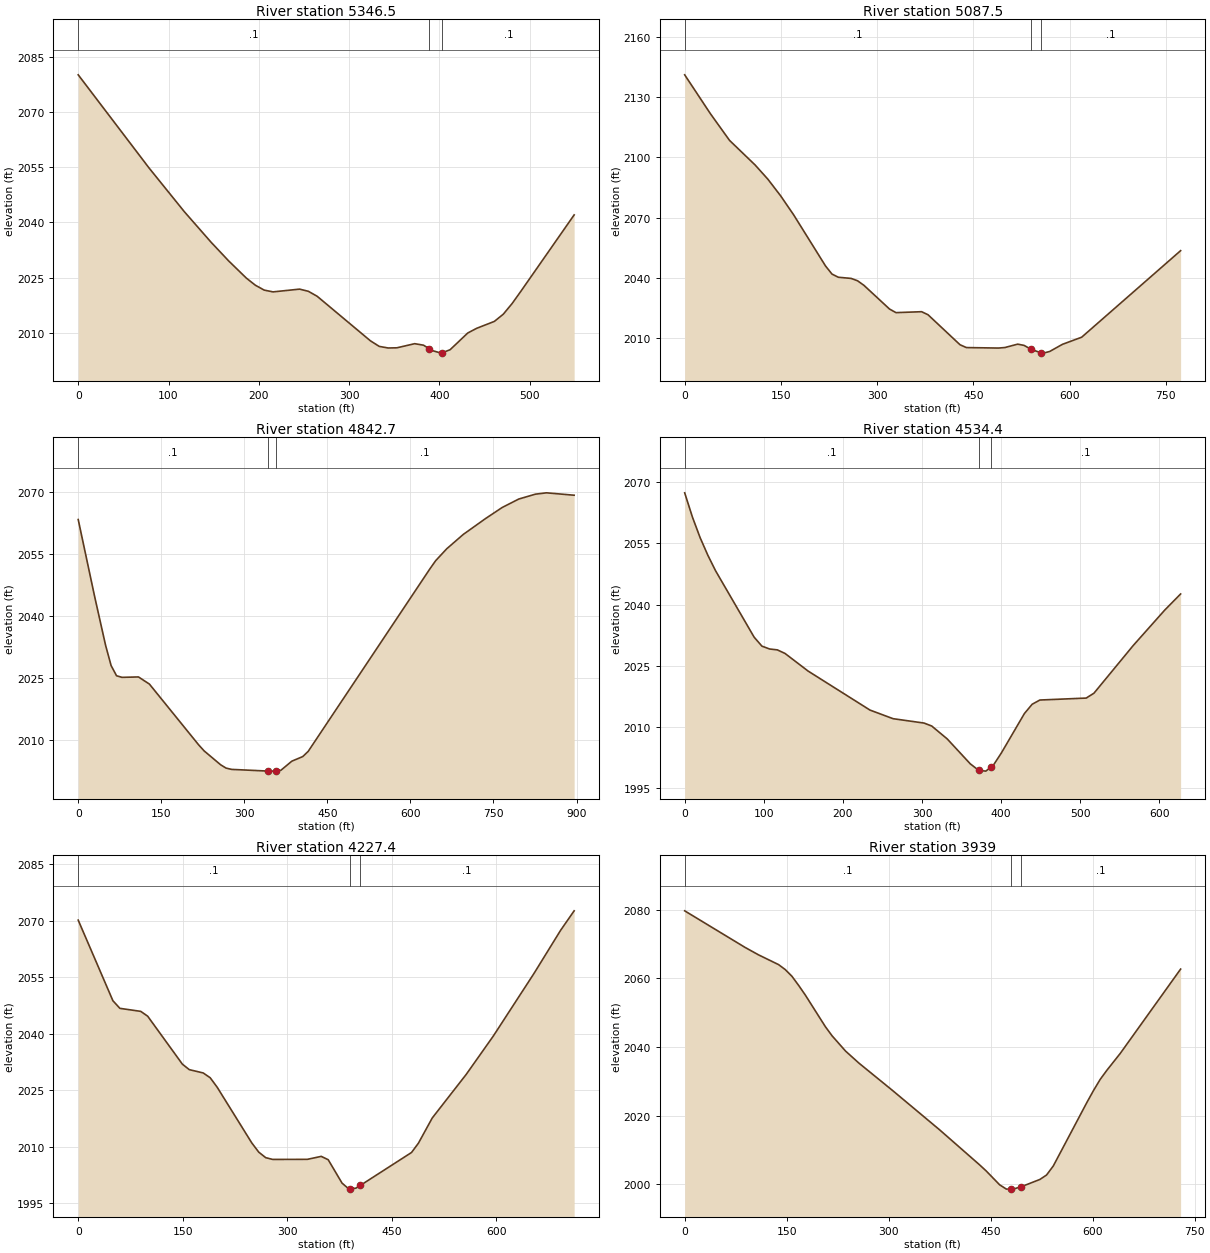
Type RM Length L Ch R = 1 ,5346.5,255.1,259,263
XS GIS Cut Line= 3
     1986401.638      401372.495     1986754.686      401124.577
     1986833.141      401036.707
#Sta/Elev= 30
       0 2080.20    78.4 2054.86   117.6 2042.92   147.1 2034.64   166.7 2029.52
   186.3 2024.84   196.1 2022.94   205.9 2021.60   215.7 2021.11   245.1 2021.86
   254.9 2021.27   264.7 2019.90   323.6 2007.79   333.4 2006.27   343.2 2005.84
   353.0 2005.89   372.6 2007.01   382.4 2006.60   388.4 2005.69   392.2 2005.12
   402.0 2004.44   403.4 2004.57   411.8 2005.36   431.4 2009.92   441.2 2011.19
   460.8 2013.07   470.7 2015.03   480.5 2017.94   490.3 2021.31   549.2 2042.07
#Mann= 3 , 0 , 0
       0     0.1       0   388.4   0.045       0   403.4     0.1       0
Bank Sta=   388.4,   403.4
Exp/Cntr=0.3,0.1

Type RM Length L Ch R = 1 ,5087.5,249.6,244.5,239.4
XS GIS Cut Line= 3
     1986373.629      401588.825     1986934.660      401327.779
     1987049.676      401224.999
#Sta/Elev= 30
       0 2140.98    39.9 2121.76    69.9 2108.41   109.8 2096.18   129.8 2089.07
   149.7 2080.80   169.7 2071.49   219.6 2045.97   229.6 2041.99   239.5 2040.40
   259.5 2039.82   269.5 2038.64   279.4 2036.38   319.4 2024.58   329.4 2022.82
   369.3 2023.28   379.3 2021.77   429.2 2006.86   439.1 2005.46   489.0 2005.22
   499.0 2005.47   519.0 2007.16   529.0 2006.54   539.9 2004.61   554.9 2002.90
   558.9 2002.70   568.9 2003.52   588.8 2007.07   618.8 2010.61   773.0 2053.61
#Mann= 3 , 0 , 0
       0     0.1       0   539.9   0.045       0   554.9     0.1       0
Bank Sta=   539.9,   554.9
Exp/Cntr=0.3,0.1

Type RM Length L Ch R = 1 ,4842.7,298.1,308.4,318.7
XS GIS Cut Line= 4
     1986712.320      401706.713     1986907.804      401636.387
     1987079.489      401502.730     1987411.434      401169.465
#Sta/Elev= 30
       0 2063.33    29.7 2044.66    49.5 2032.84    59.4 2027.97    69.2 2025.50
    79.1 2025.11   108.8 2025.21   128.6 2023.48   217.6 2008.75   227.5 2007.29
   257.2 2003.94   267.1 2003.13   277.0 2002.82   342.8 2002.41   346.2 2002.40
   357.8 2002.43   366.0 2002.60   385.8 2004.81   405.6 2005.93   415.4 2007.19
   635.5 2051.45   645.5 2053.35   665.5 2056.24   695.5 2059.73   735.6 2063.56
   765.6 2066.24   795.6 2068.29   825.6 2069.47   845.7 2069.80   895.7 2069.22
#Mann= 3 , 0 , 0
       0     0.1       0   342.8   0.045       0   357.8     0.1       0
Bank Sta=   342.8,   357.8
Exp/Cntr=0.3,0.1

Type RM Length L Ch R = 1 ,4534.4,309,307,305
XS GIS Cut Line= 4
     1986800.190      401935.802     1987093.611      401829.103
     1987303.895      401785.283     1987401.155      401763.201
#Sta/Elev= 30
       0 2067.39     9.8 2061.45    19.5 2056.42    29.3 2052.10    39.0 2048.32
    87.8 2032.04    97.6 2029.85   107.3 2029.15   117.1 2028.93   126.8 2028.06
   156.1 2023.73   234.2 2014.19   263.4 2012.08   302.5 2011.01   312.2 2010.29
   331.8 2007.13   361.0 2001.02   371.6 1999.43   380.6 1999.24   386.6 2000.17
   390.3 2000.74   400.1 2003.64   429.4 2013.35   439.2 2015.62   448.9 2016.65
   507.5 2017.13   517.3 2018.33   566.9 2030.00   606.8 2038.69   626.8 2042.62
#Mann= 3 , 0 , 0
       0     0.1       0   371.6   0.045       0   386.6     0.1       0
Bank Sta=   371.6,   386.6
Exp/Cntr=0.3,0.1

Type RM Length L Ch R = 1 ,4227.4,293.5,288.4,283.2
XS GIS Cut Line= 3
     1986864.523      402224.516     1987360.358      402073.883
     1987553.358      402058.192
#Sta/Elev= 30
       0 2070.14    49.8 2048.76    59.8 2046.74    89.7 2045.94    99.7 2044.66
   149.5 2031.94   159.4 2030.48   179.4 2029.60   189.4 2028.33   199.3 2025.86
   249.1 2011.05   259.1 2008.60   269.1 2007.13   279.0 2006.66   328.9 2006.68
   348.8 2007.47   358.8 2006.58   378.7 2000.37   388.7 1998.78   389.8 1998.81
   398.6 1999.04   404.8 1999.75   478.4 2008.50   488.3 2010.97   508.2 2017.67
   556.9 2029.22   595.7 2039.37   653.8 2055.89   692.5 2067.48   711.8 2072.61
#Mann= 3 , 0 , 0
       0     0.1       0   389.8   0.045       0   404.8     0.1       0
Bank Sta=   389.8,   404.8
Exp/Cntr=0.3,0.1

Type RM Length L Ch R = 1 ,3939,279.6,276.1,272.6
XS GIS Cut Line= 3
     1986914.734      402623.068     1987401.155      402342.199
     1987540.805      402249.622
#Sta/Elev= 30
       0 2079.66    88.7 2069.01   108.4 2066.85   138.0 2063.99   147.8 2062.55
   157.7 2060.59   167.5 2057.95   177.4 2055.11   206.9 2045.89   216.8 2043.22
   236.5 2038.80   256.2 2035.28   305.5 2027.33   374.5 2015.90   433.6 2005.64
   443.4 2003.84   463.2 1999.80   473.0 1998.57   479.7 1998.56   482.8 1998.56
   494.7 1999.25   522.3 2001.38   532.1 2002.68   542.0 2005.31   591.2 2023.75
   601.1 2027.29   611.0 2030.55   620.8 2033.20   640.5 2038.12   729.2 2062.68
#Mann= 3 , 0 , 0
       0     0.1       0   479.7   0.045       0   494.7     0.1       0
Bank Sta=   479.7,   494.7
Exp/Cntr=0.3,0.1

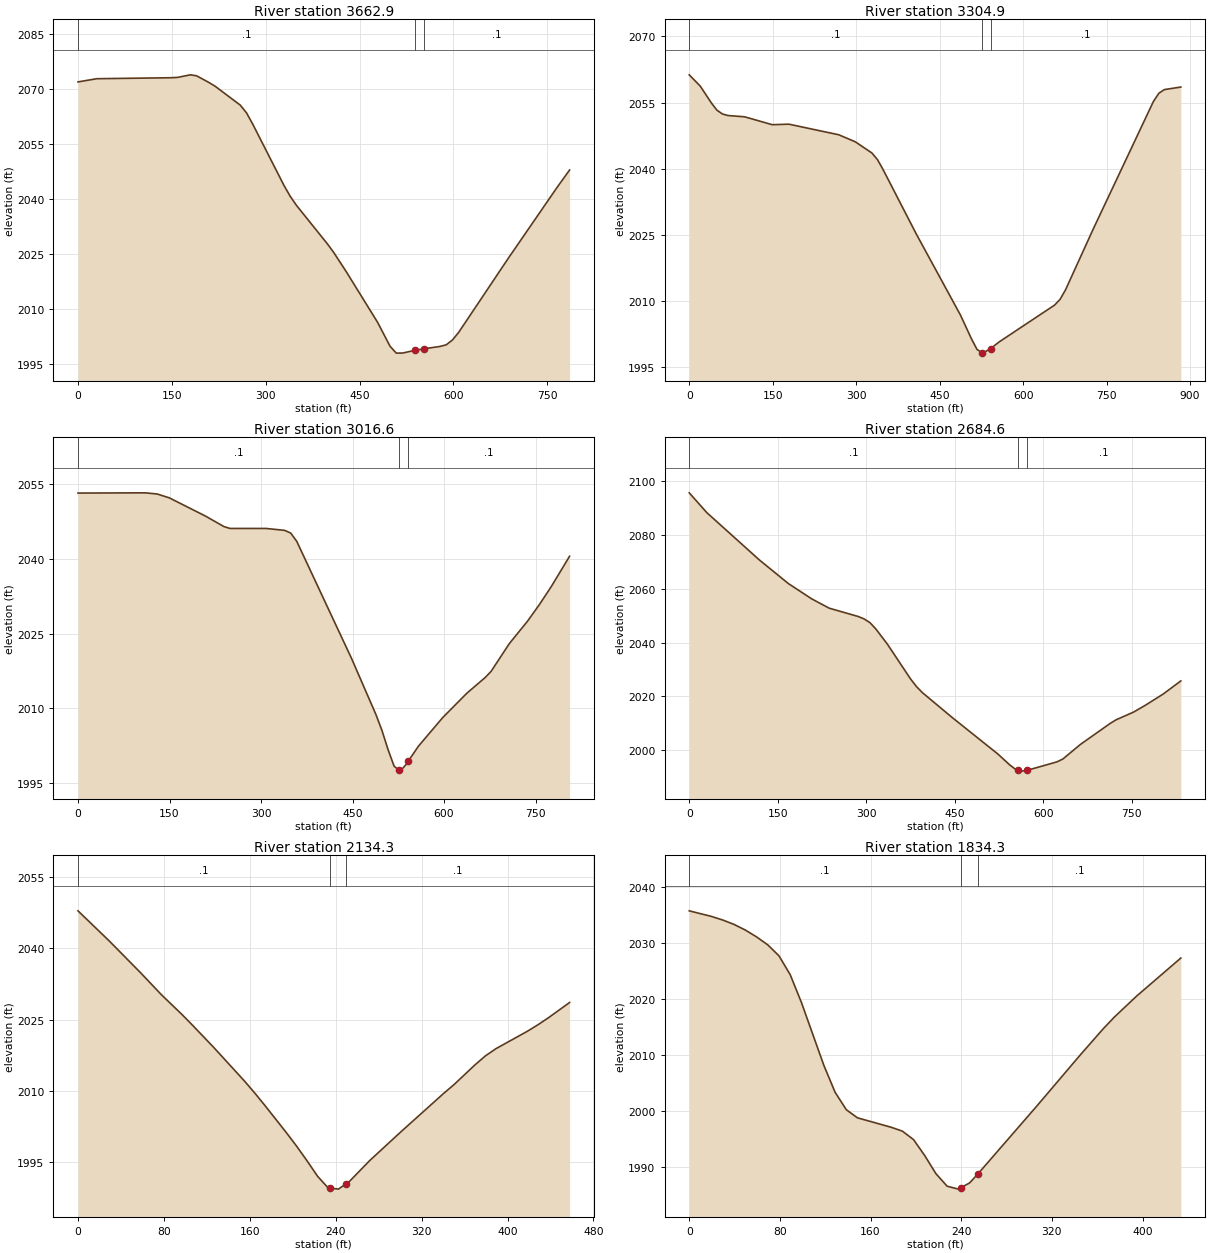
Type RM Length L Ch R = 1 ,3662.9,346.7,358,369.3
XS GIS Cut Line= 3
     1987081.729      402934.069     1987579.767      402534.481
     1987655.349      402408.101
#Sta/Elev= 30
       0 2071.89    29.9 2072.76   149.6 2073.03   159.6 2073.13   179.6 2073.82
   189.6 2073.55   209.5 2071.72   219.5 2070.68   259.4 2065.57   269.4 2063.46
   279.4 2060.38   329.2 2043.73   339.2 2040.76   349.2 2038.29   399.1 2027.71
   409.0 2025.41   429.0 2020.18   478.9 2006.45   498.8 1999.94   508.8 1998.06
   518.8 1998.08     538 1998.80     553 1999.24   578.7 1999.88   588.6 2000.32
   598.6 2001.64   608.6 2003.73   687.6 2023.82   766.2 2043.27   785.8 2047.91
#Mann= 3 , 0 , 0
       0     0.1       0     538   0.045       0     553     0.1       0
Bank Sta=     538,     553
Exp/Cntr=0.3,0.1

Type RM Length L Ch R = 1 ,3304.9,280.9,288.2,295.5
XS GIS Cut Line= 3
     1987140.516      402999.007     1987796.448      402881.299
     1988013.104      402869.416
#Sta/Elev= 30
       0 2061.30    19.9 2058.72    39.8 2054.92    49.7 2053.29    59.7 2052.42
    69.6 2052.07    99.5 2051.78   149.2 2049.99   179.0 2050.11   268.6 2047.71
   298.4 2046.11   328.2 2043.58   338.2 2042.08   348.1 2039.87   407.8 2025.25
   487.4 2006.82   507.3 2001.40   517.2 1999.02   526.4 1998.26   527.2 1998.19
   541.4 1999.19   557.0 2000.74   656.5 2009.08   666.4 2010.38   676.3 2012.57
   725.6 2026.23   834.1 2055.25   843.9 2057.12   853.8 2057.95   883.4 2058.53
#Mann= 3 , 0 , 0
       0     0.1       0   526.4   0.045       0   541.4     0.1       0
Bank Sta=   526.4,   541.4
Exp/Cntr=0.3,0.1

Type RM Length L Ch R = 1 ,3016.6,356.6,332,307.5
XS GIS Cut Line= 3
     1987133.928      403112.386     1987735.373      403200.496
     1987909.504      403106.278
#Sta/Elev= 30
       0 2053.26   109.6 2053.31   129.6 2053.08   149.5 2052.31   209.3 2048.62
   239.2 2046.53   249.1 2046.16   308.9 2046.15   338.8 2045.77   348.8 2045.22
   358.7 2043.54   448.4 2020.05   488.3 2008.81   498.2 2005.61   508.2 2001.76
   518.2 1998.40   526.3 1997.61   528.2 1997.42   538.1 1998.79   541.3 1999.42
   558.0 2002.42   597.9 2008.18   637.6 2013.09   667.3 2016.20   677.2 2017.46
   706.9 2023.01   736.6 2027.49   756.4 2030.88   776.2 2034.56   805.8 2040.58
#Mann= 3 , 0 , 0
       0     0.1       0   526.3   0.045       0   541.3     0.1       0
Bank Sta=   526.3,   541.3
Exp/Cntr=0.3,0.1

Type RM Length L Ch R = 1 ,2684.6,557.8,550.3,540.9
XS GIS Cut Line= 3
     1987537.733      403855.622     1987857.763      403404.479
     1988020.949      403176.960
#Sta/Elev= 30
       0 2095.71    29.6 2088.38   118.5 2070.81   167.9 2061.98   207.4 2056.29
   237.0 2052.82   286.4 2049.71   296.3 2048.81   306.2 2047.44   316.1 2045.11
   335.8 2039.43   375.3 2026.41   385.2 2023.62   395.1 2021.40   444.5 2012.34
   523.5 1998.48   543.2 1994.50   553.1 1992.86   557.7 1992.56   563.1 1992.20
   572.7 1992.50   623.1 1995.64   633.1 1996.69   663.1 2002.16   713.1 2009.90
   723.1 2011.26   753.1 2014.17   773.1 2016.71   803.1 2020.86   833.1 2025.75
#Mann= 3 , 0 , 0
       0     0.1       0   557.7   0.045       0   572.7     0.1       0
Bank Sta=   557.7,   572.7
Exp/Cntr=0.3,0.1

Type RM Length L Ch R = 1 ,2134.3,306.7,300,292.9
XS GIS Cut Line= 3
     1988133.433      404017.590     1988204.968      403785.913
     1988251.719      403575.694
#Sta/Elev= 30
       0 2047.95    29.1 2041.59    58.2 2034.90    77.6 2030.26    97.0 2026.03
   106.7 2023.79   126.1 2019.19   155.2 2011.98   164.9 2009.41   174.6 2006.71
   194.0 2001.14   203.7 1998.24   213.4 1995.15   223.1 1991.92   232.8 1989.50
     235 1989.43   242.5 1989.20     250 1990.36   252.3 1990.71   271.8 1995.26
   301.2 2001.40   340.4 2009.38   350.2 2011.27   369.7 2015.43   379.5 2017.34
   389.3 2018.86   418.7 2022.55   428.5 2023.92   438.2 2025.39   457.8 2028.60
#Mann= 3 , 0 , 0
       0     0.1       0     235   0.045       0     250     0.1       0
Bank Sta=     235,     250
Exp/Cntr=0.3,0.1

Type RM Length L Ch R = 1 ,1834.3,516.9,537,558.5
XS GIS Cut Line= 3
     1988499.449      403990.809     1988499.313      403743.394
     1988481.595      403557.839
#Sta/Elev= 30
       0 2035.76    19.8 2034.75    29.7 2034.11    39.6 2033.33    49.5 2032.33
    59.4 2031.11    69.3 2029.69    79.2 2027.73    89.1 2024.37    99.0 2019.41
   118.8 2008.19   128.7 2003.40   138.6 2000.29   148.4 1998.84   178.1 1997.16
   188.0 1996.47   197.9 1994.96   207.8 1992.11   217.7 1988.87   227.6 1986.64
   237.5 1986.12   239.9 1986.39   247.4 1987.23   254.9 1988.87   306.3 2000.84
   345.5 2010.16   365.1 2014.67   375.0 2016.78   394.6 2020.52   433.8 2027.34
#Mann= 3 , 0 , 0
       0     0.1       0   239.9   0.045       0   254.9     0.1       0
Bank Sta=   239.9,   254.9
Exp/Cntr=0.3,0.1

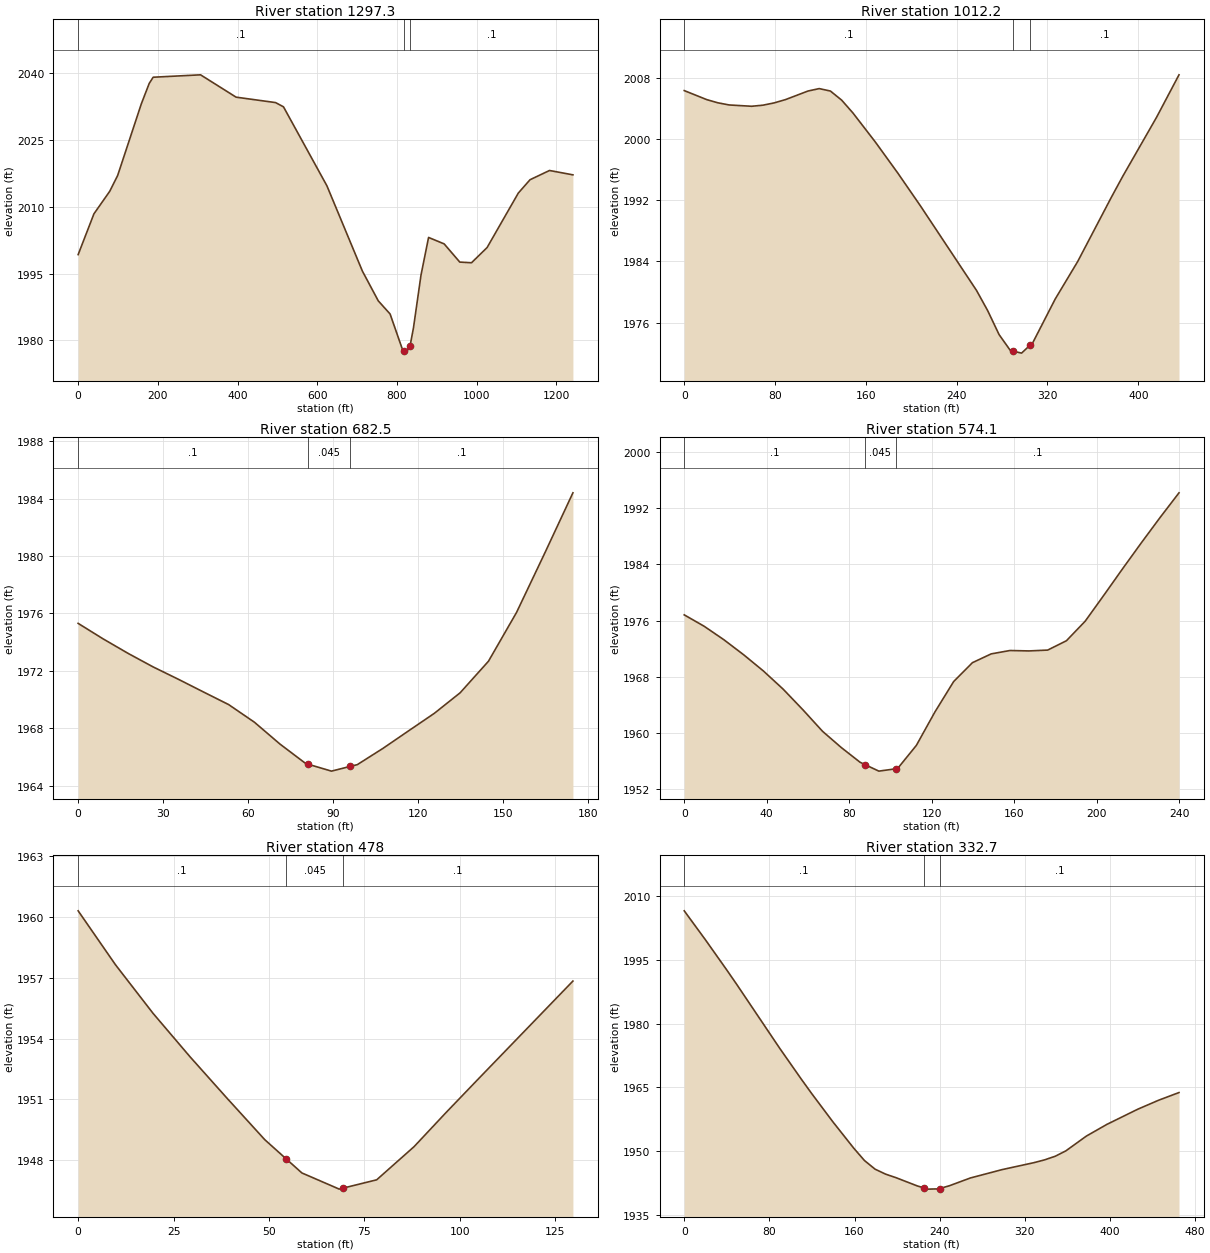
Type RM Length L Ch R = 1 ,1297.3,282.4,284.5,287.6
XS GIS Cut Line= 4
     1988322.631      404390.255     1988950.273      403859.132
     1988992.058      403820.521     1988916.796      403466.335
#Sta/Elev= 30
       0 1999.29    39.6 2008.46    79.2 2013.52    99.1 2017.07   158.5 2033.18
   178.3 2037.77   188.2 2039.16   307.1 2039.70   396.2 2034.68   495.3 2033.46
   515.1 2032.51   624.1 2014.75   713.2 1995.56   752.9 1988.90   782.6 1985.94
   812.3 1978.30   817.8 1977.66   822.2 1977.15   832.8 1978.83   841.2 1982.83
   860.1 1994.70   879.1 2003.15   918.2 2001.70   957.4 1997.61   986.8 1997.46
  1025.9 2000.88  1104.2 2013.12  1133.6 2016.12  1182.5 2018.20  1241.2 2017.22
#Mann= 3 , 0 , 0
       0     0.1       0   817.8   0.045       0   832.8     0.1       0
Bank Sta=   817.8,   832.8
Exp/Cntr=0.3,0.1

Type RM Length L Ch R = 1 ,1012.2,287.4,329.4,371.4
XS GIS Cut Line= 3
     1988887.597      404233.517     1989156.157      404047.162
     1989198.561      403946.731
#Sta/Elev= 30
       0 2006.34    19.8 2005.16    29.7 2004.74    39.6 2004.46    59.4 2004.29
    69.3 2004.43    79.2 2004.73    89.2 2005.16   109.0 2006.28   118.9 2006.60
   128.8 2006.28   138.7 2005.09   148.6 2003.42   168.4 1999.61   188.2 1995.55
   208.0 1991.29   257.5 1980.22   267.4 1977.56   277.4 1974.44   287.3 1972.37
   289.9 1972.28   297.2 1972.02   304.9 1973.09   307.1 1973.39   326.9 1979.11
   346.7 1984.01   376.4 1992.42   386.4 1995.15   416.1 2002.84   435.9 2008.40
#Mann= 3 , 0 , 0
       0     0.1       0   289.9   0.045       0   304.9     0.1       0
Bank Sta=   289.9,   304.9
Exp/Cntr=0.3,0.1

Type RM Length L Ch R = 1 ,682.5,111.8,108.3,104.9
XS GIS Cut Line= 4
     1989176.144      404262.922     1989217.262      404296.502
     1989245.359      404373.254     1989274.141      404400.666
#Sta/Elev= 22
       0 1975.31     8.8 1974.23    17.7 1973.21    26.5 1972.27    35.4 1971.41
    44.2 1970.53    53.1 1969.65    62.2 1968.42    71.2 1966.90    80.3 1965.54
      81 1965.50    89.4 1965.01      96 1965.34    98.5 1965.46   107.6 1966.60
   116.7 1967.83   125.7 1969.04   134.8 1970.47   144.8 1972.67   154.7 1976.07
   164.6 1980.18   174.6 1984.41
#Mann= 3 , 0 , 0
       0     0.1       0      81   0.045       0      96     0.1       0
Bank Sta=      81,      96
Exp/Cntr=0.3,0.1

Type RM Length L Ch R = 1 ,574.1,94.7,96.1,97.5
XS GIS Cut Line= 4
     1989121.053      404279.827     1989116.031      404346.781
     1989151.182      404410.388     1989245.569      404444.074
#Sta/Elev= 29
       0 1976.83     9.6 1975.22    19.2 1973.30    28.8 1971.16    38.4 1968.85
    48.0 1966.26    57.6 1963.32    67.1 1960.27    76.2 1957.96    85.3 1955.87
    87.6 1955.55    94.4 1954.61   102.6 1954.94   103.5 1954.98   112.6 1958.27
   121.6 1963.02   130.7 1967.35   139.8 1970.03   148.9 1971.28   158.0 1971.76
   167.2 1971.70   176.3 1971.82   185.4 1973.15   194.5 1975.93   203.6 1979.64
   212.7 1983.41   221.8 1987.10   230.9 1990.70   240.0 1994.18
#Mann= 3 , 0 , 0
       0     0.1       0    87.6   0.045       0   102.6     0.1       0
Bank Sta=    87.6,   102.6
Exp/Cntr=0.3,0.1

Type RM Length L Ch R = 1 ,478,149.4,145.3,141.3
XS GIS Cut Line= 3
     1989016.471      404356.807     1989054.162      404436.301
     1989087.741      404460.972
#Sta/Elev= 17
       0 1960.31     9.8 1957.64    19.6 1955.25    29.3 1953.10    39.1 1951.03
    48.9 1949.00    54.4 1948.07    58.6 1947.36    68.4 1946.56    69.4 1946.61
    78.2 1947.02    88.0 1948.66    96.3 1950.33   104.6 1951.96   113.0 1953.60
   121.3 1955.22   129.6 1956.84
#Mann= 3 , 0 , 0
       0     0.1       0    54.4   0.045       0    69.4     0.1       0
Bank Sta=    54.4,    69.4
Exp/Cntr=0.3,0.1

Type RM Length L Ch R = 1 ,332.7,242.1,227.8,213.5
XS GIS Cut Line= 3
     1988787.770      404311.421     1989003.697      404597.650
     1989109.150      404611.459
#Sta/Elev= 30
       0 2006.46    19.9 1999.66    39.8 1992.63    49.8 1989.01    89.6 1974.22
   109.6 1967.08   119.5 1963.64   139.4 1957.00   159.4 1950.69   169.3 1947.84
   179.3 1945.80   189.2 1944.63   199.2 1943.78   219.1 1941.85   225.1 1941.41
   229.1 1941.11   239.0 1941.17   240.1 1941.25   249.0 1941.89   268.9 1943.73
   298.8 1945.70   328.7 1947.33   338.6 1947.98   348.6 1948.83   358.5 1950.08
   377.9 1953.57   397.2 1956.32   426.2 1959.88   445.6 1961.97   464.9 1963.79
#Mann= 3 , 0 , 0
       0     0.1       0   225.1   0.045       0   240.1     0.1       0
Bank Sta=   225.1,   240.1
Exp/Cntr=0.3,0.1