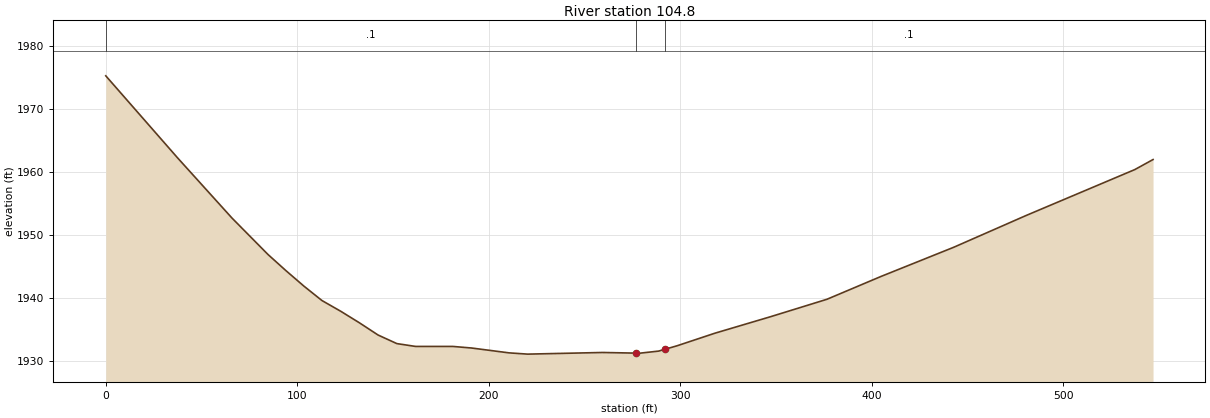
HEC-RAS study GladeCrk1.prj: GladeCrk1

--- GladeCrk1.g01 (geometry) --- (continued)

Type RM Length L Ch R = 1 ,104.8,104.9,104.7,104.6
XS GIS Cut Line= 4
     1988623.733      404572.751     1988695.708      404659.792
     1988946.201      404741.922     1989110.824      404698.290
#Sta/Elev= 30
       0 1975.22    37.6 1962.17    65.9 1952.66    84.7 1946.88    94.1 1944.31
   103.5 1941.85   112.9 1939.57   122.7 1937.87   132.5 1936.03   142.2 1934.10
   152.0 1932.74   161.8 1932.29   181.3 1932.29   191.0 1932.04   210.6 1931.27
   220.3 1931.07   259.4 1931.33   276.8 1931.23   278.9 1931.22   288.7 1931.55
   291.8 1931.82   298.4 1932.40   318.0 1934.38   347.3 1937.02   376.6 1939.77
   404.9 1943.40   442.8 1948.02   480.6 1953.06   537.4 1960.35   546.9 1961.94
#Mann= 3 , 0 , 0
       0     0.1       0   276.8   0.045       0   291.8     0.1       0
Bank Sta=   276.8,   291.8
Exp/Cntr=0.3,0.1